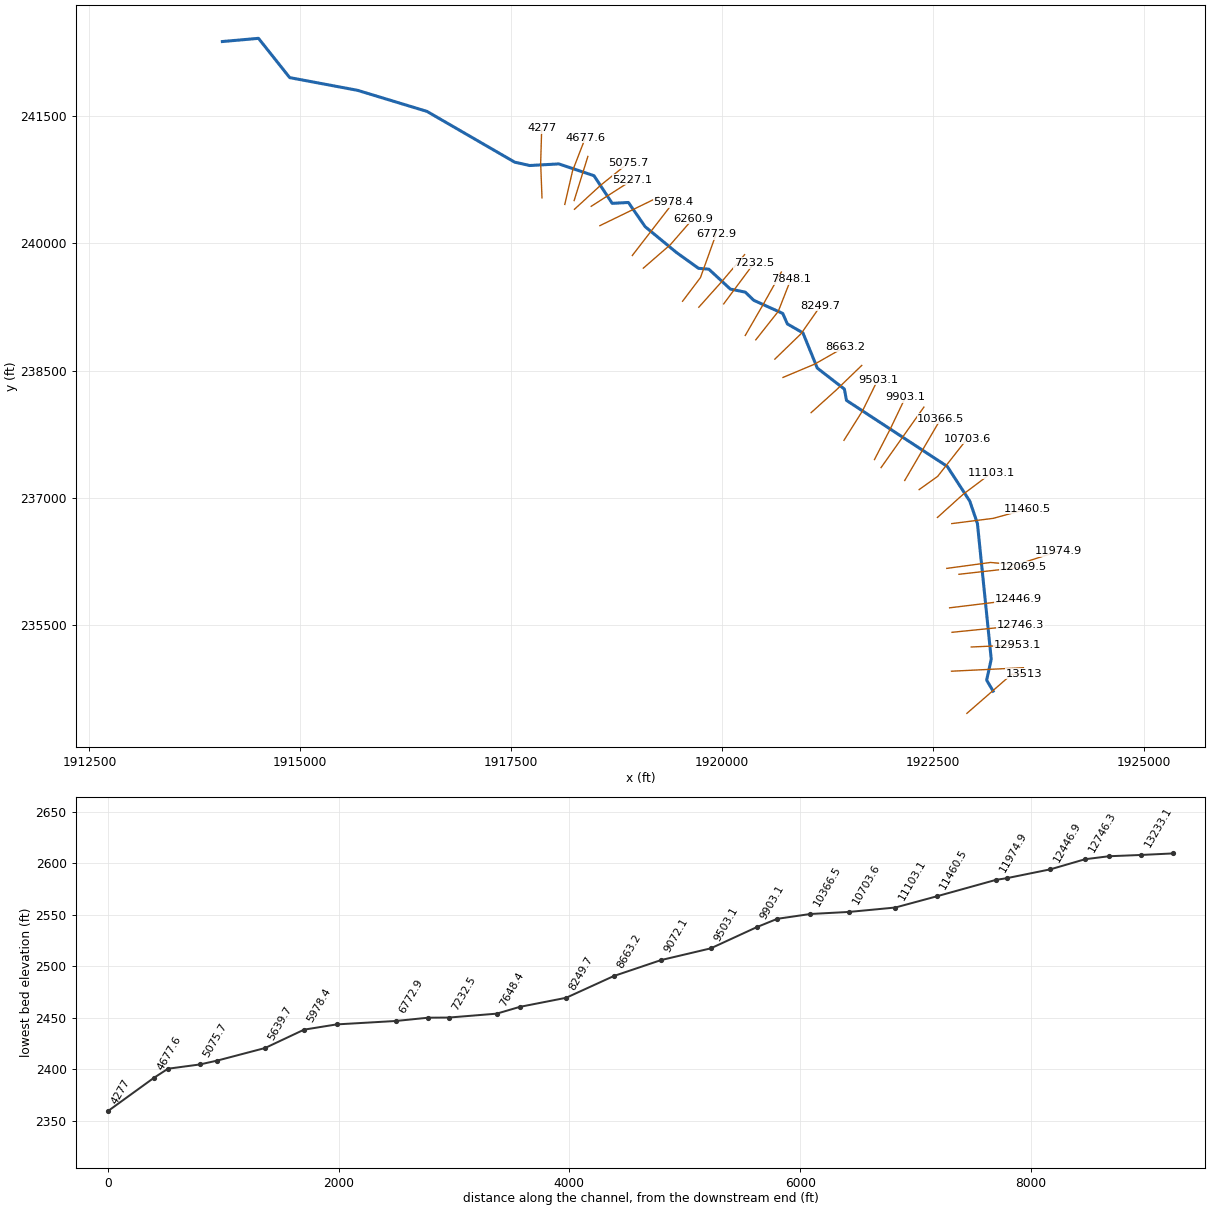
--- BwyrCrk.prj (project) ---

Proj Title=BwyrCrk
Current Plan=p01
Default Exp/Contr=0,0
English Units
Geom File=g01
Flow File=f01
Plan File=p01
BEGIN DESCRIPTION:
END DESCRIPTION:
DSS Export Rating Curves= 0
DSS Export Rating Curve Sorted= 0
DSS Export Volume Flow Curves= 0
DXF OffsetX= 0
DXF OffsetY= 0
DXF ScaleX= 0
DXF ScaleY= 0

--- BwyrCrk.p01 (plan) ---

Plan Title=Floodplain
Program Version=4.00
Geom File=g01
Flow File=f01
K Sum by GR=0
Std Step Tol=0.01
Critical Tol=0.01
Num of Std Step Trials=20
Max Error Tol=0.3
Flow Tol Ratio=0.001
Split Flow NTrial=30
Split Flow Tol=0.02
Split Flow Ratio=0.02
Log Output Level=0
Friction Slope Method=1
Unsteady Friction Slope Method=2
Unsteady Bridges Friction Slope Method=1
Global Log Level=0
CheckData=False
Run HTab=0
Run UNet=0
Run PostProcess=0
UNET Theta=0
UNET Theta Warmup=0
UNET ZTol=0
UNET ZSATol=0
UNET MxIter=0
UNET MaxInSteps=0
UNET DtIC=0
UNET DtMin=0
UNET MaxCRTS=0
UNET WFStab=0
UNET SFStab=0
UNET WFX=0
UNET SFX=0
UNET DSS MLevel=0
UNET DZMax Abort=0
UNET Convert EG Bridges=0
UNET Use Existing IB Tables=0
UNET Froude Limit=0
UNET Froude Power=0
Write IC File=0
Echo Input=False
Echo Output=False
Write Detailed=0

--- BwyrCrk.f01 (steady flow) ---

Flow Title=NFF Regression Equation
Program Version=4.10
Number of Profiles= 1
Profile Names=P100yr
River Rch & RM=BwyrCrk,Main            ,13513
527.4236
River Rch & RM=BwyrCrk,Main            ,11460.5
551.9811
River Rch & RM=BwyrCrk,Main            ,11103.1
663.2642
River Rch & RM=BwyrCrk,Main            ,7848.1
734.2531
River Rch & RM=BwyrCrk,Main            ,7648.4
814.6597
River Rch & RM=BwyrCrk,Main            ,5639.7
849.5536
River Rch & RM=BwyrCrk,Main            ,1896.9
943.2985
River Rch & RM=BwyrCrk,Main            ,1496.2
1048.655
Boundary for River Rch & Prof#=BwyrCrk,Main            , 1
Up Type= 0
Dn Type= 1
Dn Known WS=2299.5
DSS Import GetInterval= 0
DSS Import GetPeak= 0
DSS Import FillOption= 0

--- BwyrCrk.g01 (geometry) ---

Geom Title=USGS 3m DEM
Program Version=4.10

River Reach=BwyrCrk         ,Main
Reach XY= 30
     1923213.849      234714.955     1923137.099      234844.566
     1923191.445      235092.483     1923027.623       236693.55
     1922937.751      236956.669     1922669.432      237368.284
     1921475.001      238147.239     1921450.334      238280.771
     1921129.138      238528.531      1920958.84      238944.128
     1920774.141      239049.729     1920719.538      239173.672
     1920375.781      239328.837      1920275.37      239425.075
     1920097.922      239461.321       1919843.2      239695.952
     1919720.486      239706.439     1919457.052      239894.992
     1919087.926      240198.106     1918889.523      240483.487
     1918697.324      240473.221     1918481.777      240799.312
     1918064.962      240938.695     1917719.154      240919.742
     1917541.334      240959.548     1916501.009      241558.732
     1915679.116      241807.136      1914873.72      241957.366
     1914503.804      242421.085     1914075.262      242383.321

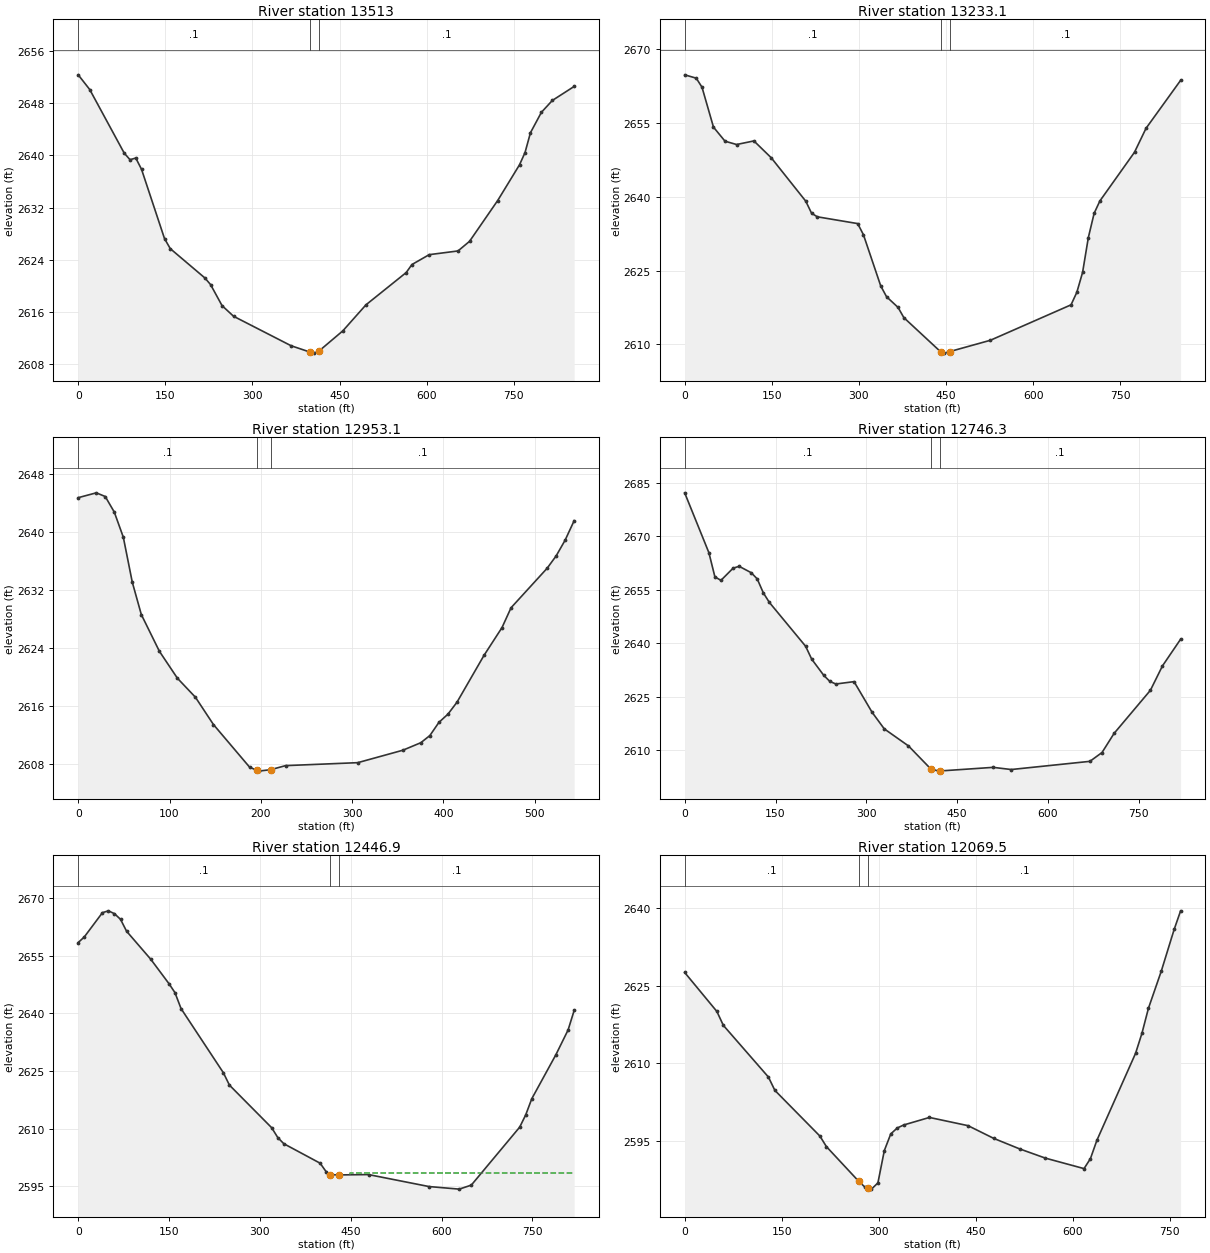
Type RM Length L Ch R = 1 ,13513   ,294.6,279.9,265.1
XS GIS Cut Line= 3
     1922902.785      234452.613     1923433.616      234913.956
     1923583.991      234918.669
#Sta/Elev= 30
       0 2652.36    19.8 2650.11    79.2 2640.36    89.2 2639.35    99.1 2639.61
     109 2637.88   148.6 2627.25   158.5 2625.72   217.9 2621.24   227.8 2620.22
   247.6 2616.99   267.4 2615.36   366.5 2610.84   399.3 2609.86   406.1 2609.71
   414.3 2610.02   455.6 2613.13   495.3 2617.11   564.6 2622.06   574.5 2623.29
   604.2  2624.8   653.8 2625.37   673.6 2626.84   722.1  2633.1   759.7 2638.58
   769.1 2640.44   778.5 2643.49   797.3 2646.61   816.1 2648.43   853.7 2650.58
#Mann= 3 , 0 , 0
       0      .1       0   399.3    .045       0   414.3      .1       0
Bank Sta=399.3,414.3
XS Rating Curve= 0 ,0
Exp/Cntr=0.3,0.1

Type RM Length L Ch R = 1 ,13233.1 ,280.6,280,279.3
XS GIS Cut Line= 2
     1922719.854      234950.372     1923572.881       234991.55
#Sta/Elev= 30
       0  2664.8    19.9 2664.12    29.8 2662.29    49.6 2654.16    69.5  2651.3
    89.4 2650.63   119.2 2651.36     149 2647.94   208.5 2639.11   218.5 2636.66
   228.4 2635.93   297.9 2634.55   307.8 2632.29   337.6 2621.88   347.6 2619.68
   367.4 2617.51   377.4 2615.43   441.9 2608.36   446.9 2608.21   456.9 2608.54
   526.3 2610.82   665.3 2618.03   675.3 2620.58   685.2 2624.63   695.1 2631.71
   705.1 2636.65     715 2639.16   774.6 2649.06   794.4 2653.92     854 2663.68
#Mann= 3 , 0 , 0
       0      .1       0   441.9    .045       0   456.9      .1       0
Bank Sta=441.9,456.9
XS Rating Curve= 0 ,0
Exp/Cntr=0.3,0.1

Type RM Length L Ch R = 1 ,12953.1 ,205.6,206.9,208.2
XS GIS Cut Line= 2
      1922954.74      235236.242     1923497.345      235259.912
#Sta/Elev= 30
       0 2644.76    19.8 2645.43    29.6 2644.92    39.5 2642.77    49.4 2639.29
    59.2 2633.08    69.1  2628.6    88.9 2623.52   108.6  2619.8   128.4 2617.16
   148.1 2613.39   187.6 2607.51   195.7 2607.05   197.5 2606.95   210.7 2607.15
   227.1 2607.71   306.1 2608.12   355.5 2609.84   375.2 2610.88   385.1 2611.87
     395 2613.69   404.9 2614.83   414.8 2616.48   444.4 2622.96   464.1  2626.8
     474 2629.54   513.5    2635   523.4 2636.71   533.2 2638.88   543.1 2641.58
#Mann= 3 , 0 , 0
       0      .1       0   195.7    .045       0   210.7      .1       0
Bank Sta=195.7,210.7
XS Rating Curve= 0 ,0
Exp/Cntr=0.3,0.1

Type RM Length L Ch R = 1 ,12746.3 ,298.9,299.4,299.8
XS GIS Cut Line= 3
     1922726.234      235409.595     1923133.675      235450.604
     1923541.116      235491.614
#Sta/Elev= 30
       0 2682.25      40 2665.42    49.9 2658.63    59.9 2657.65    79.9 2661.06
    89.9  2661.6   109.9  2659.8   119.8 2658.06   129.8 2654.16   139.8 2651.46
   199.8 2639.11   209.7 2635.52   229.7 2630.95   239.7 2629.25   249.7 2628.52
   279.7 2629.18   309.6 2620.54   329.6 2615.91   369.6 2611.11   406.3 2604.67
   419.5 2604.03   421.3 2604.07   509.4 2605.09   539.3 2604.48   669.2 2606.78
   689.2 2609.26   709.1 2614.63   769.1 2626.75     789  2633.6     819 2641.11
#Mann= 3 , 0 , 0
       0      .1       0   406.3    .045       0   421.3      .1       0
Bank Sta=406.3,421.3
XS Rating Curve= 0 ,0
Exp/Cntr=0.3,0.1

Type RM Length L Ch R = 1 ,12446.9 ,377.6,377.4,377.2
XS GIS Cut Line= 3
     1922697.877      235698.682     1923104.402       235747.95
     1923510.928      235797.217
#Sta/Elev= 30
       0 2658.46      10 2659.91      40 2666.24    49.9 2666.72    59.9 2665.97
    69.9  2664.5    79.9  2661.4   119.8 2654.11   149.8 2647.77   159.8 2645.41
   169.8 2641.27   239.7 2624.56   249.7 2621.34   319.6 2610.22   329.6 2607.67
   339.6 2606.07   399.5    2601   409.5 2598.77   416.1 2598.02   431.1 2597.95
   479.4 2598.04   579.3 2594.92   629.2 2594.25   649.2  2595.3   729.1  2610.4
   739.1 2613.62   749.1 2617.81     789  2629.3     809  2635.7     819 2640.77
#Mann= 3 , 0 , 0
       0      .1       0   416.1    .045       0   431.1      .1       0
#XS Ineff= 2 , 0
                          449.13         2598.48
Permanent Ineff=
       F       F
Bank Sta=416.1,431.1
XS Rating Curve= 0 ,0
Exp/Cntr=0.3,0.1

Type RM Length L Ch R = 1 ,12069.5 ,94,94.6,95.1
XS GIS Cut Line= 2
     1922808.554      236094.462     1923570.884      236179.886
#Sta/Elev= 30
       0 2627.57    49.8 2620.03    59.8 2617.34   129.5 2607.34   139.5 2604.76
   209.2 2595.91   219.2 2593.88     269 2587.19     279 2586.02     284 2585.83
   288.9 2585.65   298.9 2586.86   308.8 2593.11   318.8 2596.34   328.8 2597.48
   338.7 2598.06   378.6 2599.52   438.3 2597.93   478.2 2595.46     518 2593.44
   557.9 2591.65   617.7 2589.62   627.6 2591.55   637.6  2595.1   697.4 2611.92
   707.3 2615.81   717.3 2620.63   737.2 2627.83   757.1  2635.9   767.1  2639.5
#Mann= 3 , 0 , 0
       0      .1       0     269    .045       0     284      .1       0
Bank Sta=269,284
XS Rating Curve= 0 ,0
Exp/Cntr=0.3,0.1

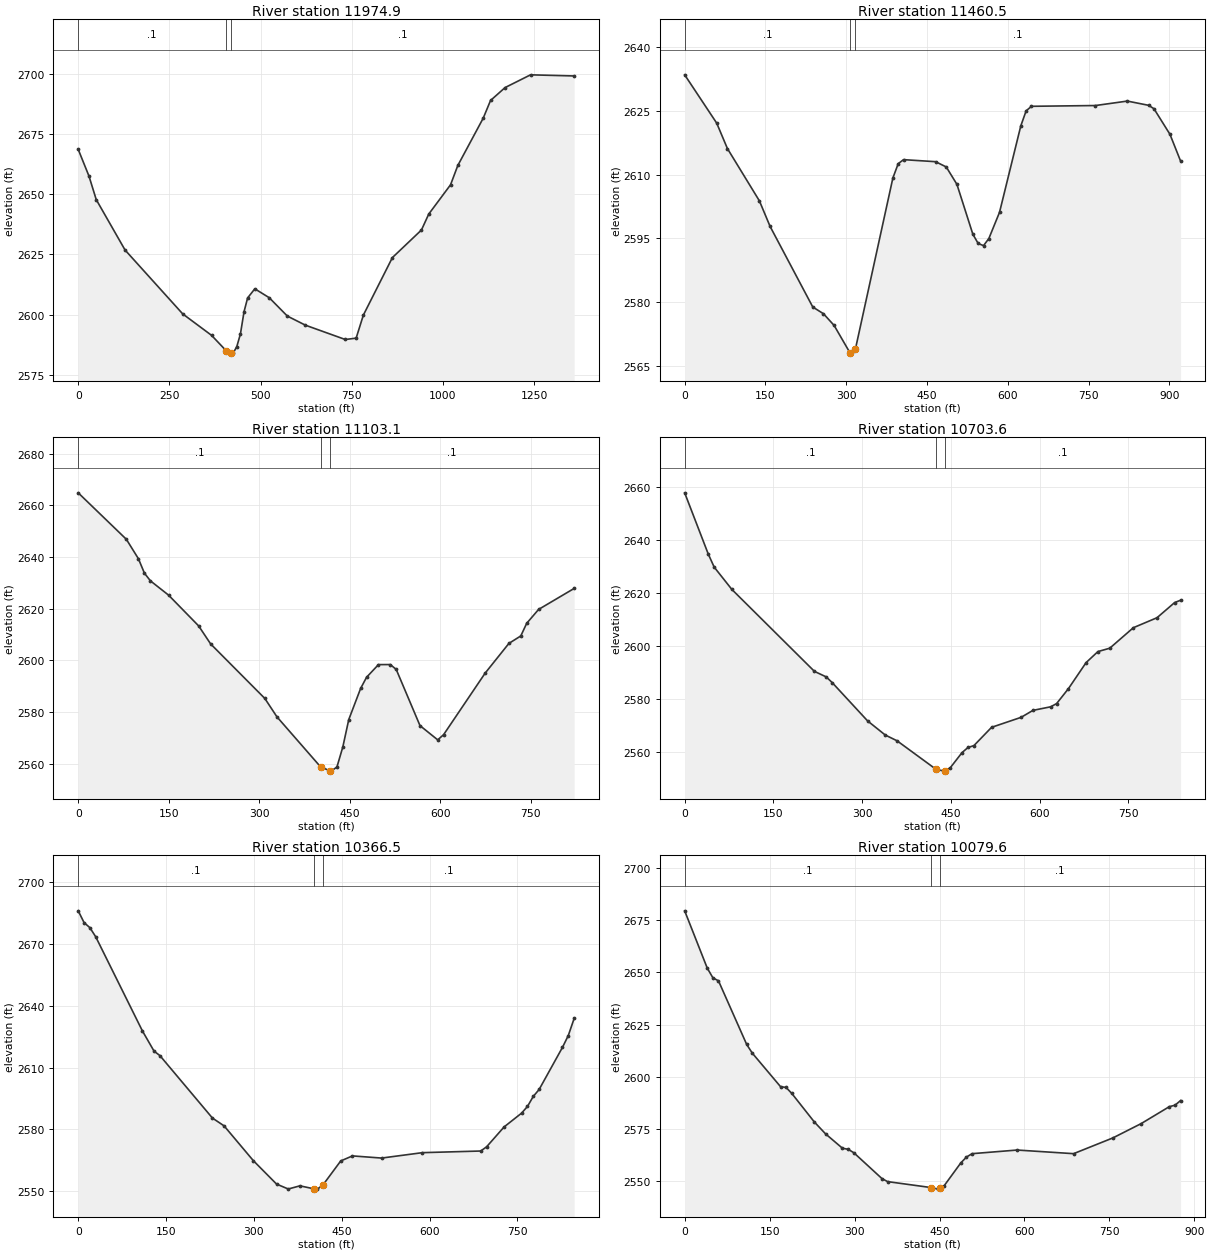
Type RM Length L Ch R = 1 ,11974.9 ,514.6,514.5,514.3
XS GIS Cut Line= 4
     1922664.372      236164.196     1923183.528      236234.116
      1923490.01      236206.402     1923993.102      236367.753
#Sta/Elev= 30
       0  2668.6    29.6 2657.46    49.4 2647.74   128.5 2626.79   286.6 2600.27
   365.7 2591.37   405.1 2585.08   420.1    2584     425 2583.99   434.9 2586.72
   444.8 2591.94   454.7 2601.18   464.5  2606.9   484.3  2610.7   523.8    2607
   573.5 2599.37   623.1 2595.59   732.3 2589.65   762.1 2590.21   781.9 2599.78
   861.5 2623.66   941.2 2635.12   961.2 2641.73    1021  2653.9  1040.9 2661.91
  1110.7  2681.6  1130.6 2688.89  1170.5 2694.26  1240.3 2699.55  1359.9 2699.08
#Mann= 3 , 0 , 0
       0      .1       0   405.1    .045       0   420.1      .1       0
Bank Sta=405.1,420.1
XS Rating Curve= 0 ,0
Exp/Cntr=0.3,0.1

Type RM Length L Ch R = 1 ,11460.5 ,343.6,357.4,369.2
XS GIS Cut Line= 3
     1922723.495      236692.899     1923215.117      236754.807
     1923625.116      236867.323
#Sta/Elev= 30
       0 2633.48    59.5  2622.1    79.3 2616.13   138.7 2603.81   158.6 2597.78
   237.8 2578.82   257.7 2577.23   277.5 2574.47   307.2 2567.96   317.1 2568.99
   386.5 2609.18   396.4 2612.56   406.3 2613.51   465.8 2613.03   485.6 2611.79
   505.4  2607.7     535 2595.95   544.9 2593.77   554.8 2593.27   564.7 2594.94
   584.5 2601.11     624 2621.46   633.9    2625   643.8 2626.07   762.5 2626.25
   821.8  2627.3   861.3  2626.3   871.2  2625.5   900.9 2619.48   920.7 2613.16
#Mann= 3 , 0 , 0
       0      .1       0   307.2    .045       0   317.1      .1       0
Bank Sta=307.2,317.1
XS Rating Curve= 0 ,0
Exp/Cntr=0.3,0.1

Type RM Length L Ch R = 1 ,11103.1 ,395.2,399.5,405.7
XS GIS Cut Line= 3
     1922553.695       236765.28     1922858.052       237038.41
     1923188.114      237286.106
#Sta/Elev= 30
       0  2664.8    79.8 2646.81    99.7 2639.32   109.7 2633.71   119.7 2630.73
   149.6 2625.24   199.5 2613.32   219.4 2606.34   309.2 2585.24   329.2 2578.14
   401.4 2558.81   416.4 2557.31   418.8 2557.13   428.6 2558.71   438.4 2566.51
   448.2 2577.07   467.9 2589.14   477.7 2593.44   497.4 2598.34     517 2598.36
   526.8 2596.49   566.2 2574.74   595.6 2569.22   605.4 2571.26   674.2 2595.06
   713.5 2606.54   733.2 2609.43     743 2614.32   762.7 2619.69   821.6 2627.81
#Mann= 3 , 0 , 0
       0      .1       0   401.4    .045       0   416.4      .1       0
Bank Sta=401.4,416.4
XS Rating Curve= 0 ,0
Exp/Cntr=0.3,0.1

Type RM Length L Ch R = 1 ,10703.6 ,334,337,340.1
XS GIS Cut Line= 3
     1922336.503      237094.161      1922555.98      237250.071
      1922908.23      237697.318
#Sta/Elev= 30
       0 2657.68    39.9  2634.6    49.9 2629.69    79.8 2621.29   219.4 2590.43
   239.3 2588.35   249.3 2586.23   309.2 2571.79   339.1 2566.46   359.1 2564.28
   424.8 2553.57     439 2552.86   439.8 2552.96     449 2554.12     469 2559.85
     479 2561.76     489 2562.47   518.9 2569.36   568.8 2573.12   588.8 2575.74
   618.8 2577.09   628.8 2578.29   648.8 2583.92   678.7 2593.74   698.7 2597.89
   718.7 2599.16   758.6 2606.88   798.6 2610.64   828.5 2616.37   838.5 2617.22
#Mann= 3 , 0 , 0
       0      .1       0   424.8    .045       0   439.8      .1       0
Bank Sta=424.8,439.8
XS Rating Curve= 0 ,0
Exp/Cntr=0.3,0.1

Type RM Length L Ch R = 1 ,10366.5 ,288.9,286.9,284.9
XS GIS Cut Line= 2
      1922165.51      237201.644     1922594.217      237931.969
#Sta/Elev= 30
       0 2686.22      10 2680.49    19.9 2678.03    29.9 2673.59   109.6 2627.81
   129.5 2617.97   139.5  2615.8   229.2 2585.41   249.1 2581.61   298.9 2564.74
   338.7  2553.3   358.7  2550.9   378.6 2552.44     403 2550.96   408.5 2550.84
     418 2552.89   448.3 2564.55   468.3    2567   518.1 2565.95   587.8 2568.58
   687.4 2569.38   697.4 2571.43   727.3  2581.1   757.2 2587.82   767.2 2591.07
   777.1 2595.95   787.1 2599.32   826.9 2619.77   836.9 2625.56   846.9 2633.87
#Mann= 3 , 0 , 0
       0      .1       0     403    .045       0     418      .1       0
Bank Sta=403,418
XS Rating Curve= 0 ,0
Exp/Cntr=0.3,0.1

Type RM Length L Ch R = 1 ,10079.6 ,173.4,176.5,180.4
XS GIS Cut Line= 2
      1921885.31      237354.161     1922392.713      238067.924
#Sta/Elev= 30
       0 2679.49    39.8 2652.07    49.8  2647.4    59.7 2645.94   109.5 2615.46
   119.4  2611.3   169.2 2595.26   179.1 2594.84   189.1 2592.01   228.9 2578.33
   248.8 2572.61   278.6 2565.73   288.6 2565.24   298.6 2563.59   348.3  2551.2
   358.3 2549.74   435.3 2546.88   447.8 2546.14   450.3 2546.51   457.8 2547.63
   487.6 2558.71   497.6 2561.52   507.5 2563.13   587.1 2564.87   686.7 2563.13
   756.3  2570.7   806.1 2577.55   855.8 2585.66   865.8 2586.35   875.7  2588.6
#Mann= 3 , 0 , 0
       0      .1       0   435.3    .045       0   450.3      .1       0
Bank Sta=435.3,450.3
XS Rating Curve= 0 ,0
Exp/Cntr=0.3,0.1

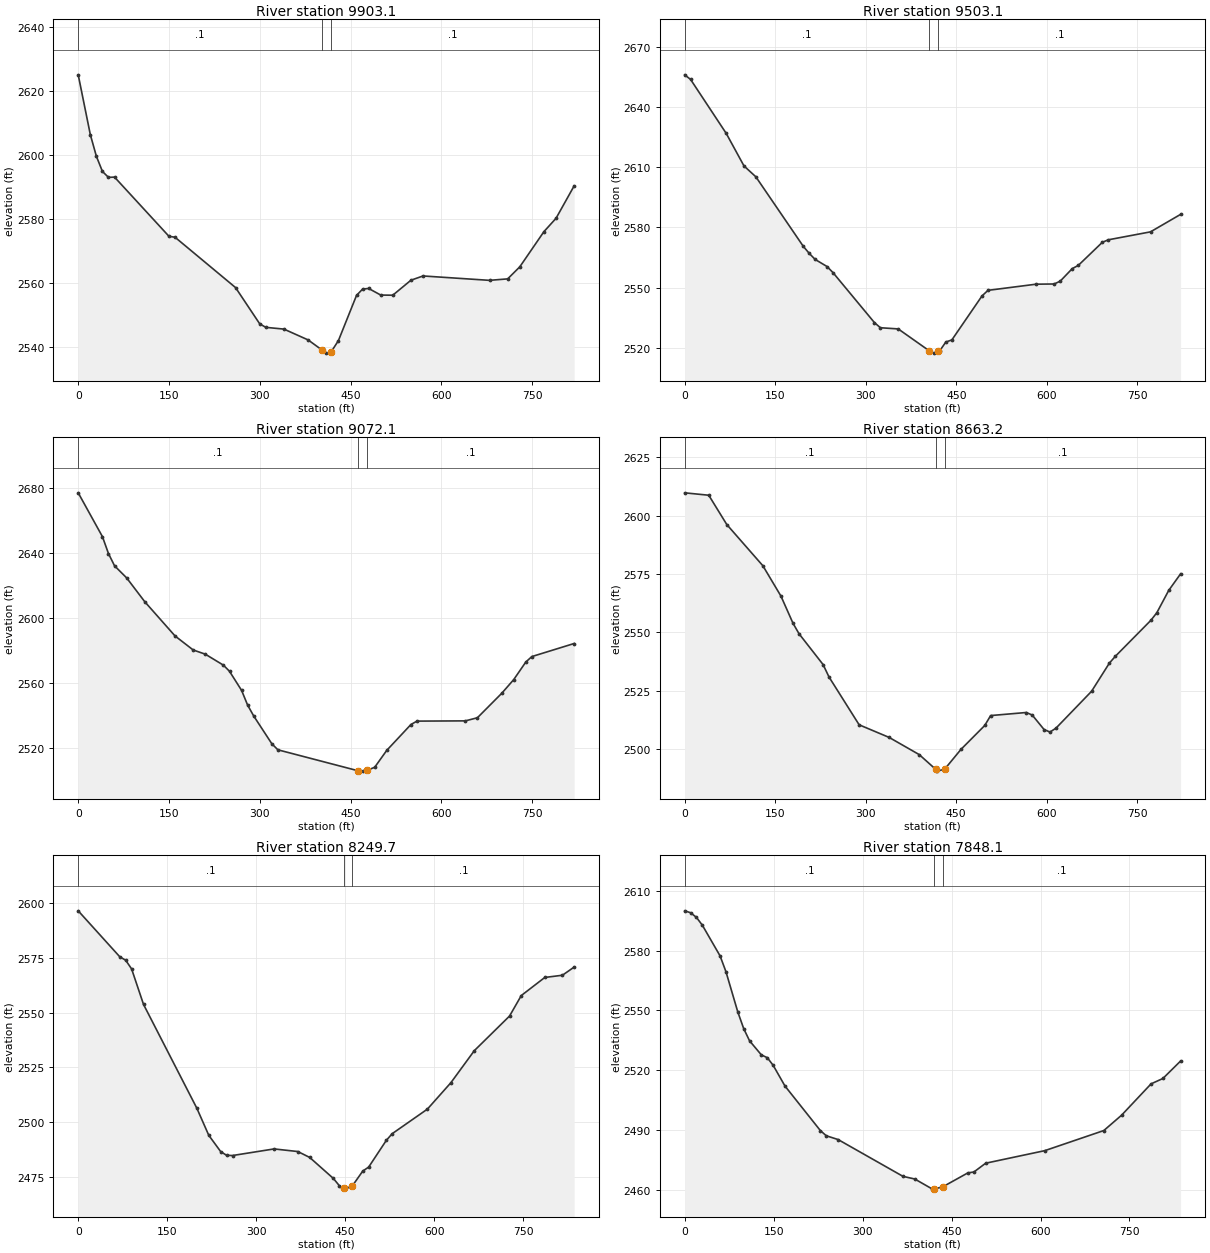
Type RM Length L Ch R = 1 ,9903.1  ,401.8,399.9,399.8
XS GIS Cut Line= 3
     1921806.887      237448.629     1921995.592      237812.395
     1922173.084      238181.377
#Sta/Elev= 30
       0 2624.97      20 2606.31      30 2599.55      40 2594.81      50 2592.96
      60 2593.04   149.9 2574.56   159.9 2574.27   259.9 2558.55   299.8 2547.24
   309.8 2546.14   339.8 2545.59   379.8 2542.21   402.3 2539.12   409.8 2538.09
   417.3 2538.34   429.8 2541.99   459.7  2556.1   469.7 2558.08   479.7 2558.28
   499.7 2556.22   519.6 2556.17   549.6 2560.85   569.6 2562.18   679.4 2560.81
   709.4 2561.27   729.4 2565.03   769.3 2576.02   789.3 2580.19   819.2 2590.31
#Mann= 3 , 0 , 0
       0      .1       0   402.3    .045       0   417.3      .1       0
Bank Sta=402.3,417.3
XS Rating Curve= 0 ,0
Exp/Cntr=0.3,0.1

Type RM Length L Ch R = 1 ,9503.1  ,436.8,430.9,422.5
XS GIS Cut Line= 3
     1921445.297      237675.932     1921665.854      238024.821
     1921846.669      238391.631
#Sta/Elev= 30
       0 2655.98     9.8 2653.68    68.8 2626.84    98.3 2610.61   117.9 2605.22
   196.6 2570.57   206.4 2567.09   216.2 2564.08   235.9 2560.54   245.7 2557.54
   314.5  2532.6   324.3 2530.08   353.8 2529.49   405.3 2518.58   412.8 2517.44
   420.3 2518.36   422.7 2518.65   432.7 2522.97   442.7 2524.02   492.6  2545.9
   502.5 2548.69   582.3 2551.76   612.2 2551.86   622.2 2553.26   642.2 2559.52
   652.2 2561.12     692 2572.61     702 2573.86   771.8 2577.81   821.7 2586.52
#Mann= 3 , 0 , 0
       0      .1       0   405.3    .045       0   420.3      .1       0
Bank Sta=405.3,420.3
XS Rating Curve= 0 ,0
Exp/Cntr=0.3,0.1

Type RM Length L Ch R = 1 ,9072.1  ,415.1,408.3,402.6
XS GIS Cut Line= 3
     1921055.793      238002.403     1921360.699       238276.18
     1921655.961      238559.852
#Sta/Elev= 30
       0 2677.26      40 2650.31      50 2639.88      60 2632.36      80 2624.93
   109.9 2610.28   159.9 2589.22   189.9 2580.58   209.9    2578   239.9 2571.22
   249.9 2567.47   269.9 2555.69   279.8 2546.69   289.8 2540.02   319.8 2522.89
   329.8 2519.16   462.4 2506.25   469.7 2506.04   477.4 2506.57   489.7  2508.4
   509.6 2518.79   549.6 2534.72   559.6 2536.81   639.5 2536.96   659.4 2538.88
   699.4 2553.85   719.4 2562.36   739.3 2573.14   749.3 2576.52   819.2 2584.56
#Mann= 3 , 0 , 0
       0      .1       0   462.4    .045       0   477.4      .1       0
Bank Sta=462.4,477.4
XS Rating Curve= 0 ,0
Exp/Cntr=0.3,0.1

Type RM Length L Ch R = 1 ,8663.2  ,402.4,413.6,423.6
XS GIS Cut Line= 3
     1920722.098      238418.012     1921099.232      238575.872
     1921458.518      238780.036
#Sta/Elev= 30
       0 2609.78    39.9 2608.75    69.8  2596.2   129.6 2578.55   159.6 2565.54
   179.5 2553.95   189.5 2549.44   229.4 2536.24   239.3 2530.88   289.2 2510.42
     339 2505.01   388.9 2497.64     416 2491.38   418.7 2490.58     431 2491.42
     458  2499.9   497.4 2510.13   507.2 2514.38   566.3 2515.69   576.1 2514.61
   595.8 2508.38   605.6 2507.32   615.5 2508.99   674.5 2524.78     704 2536.84
   713.8 2539.74   772.9  2555.2   782.7 2558.44   802.4 2567.99   822.1  2575.1
#Mann= 3 , 0 , 0
       0      .1       0     416    .045       0     431      .1       0
Bank Sta=416,431
XS Rating Curve= 0 ,0
Exp/Cntr=0.3,0.1

Type RM Length L Ch R = 1 ,8249.7  ,403.6,401.6,406.8
XS GIS Cut Line= 3
     1920625.984      238634.429     1920935.627      238933.133
     1921168.744       239265.22
#Sta/Elev= 30
       0 2596.39      70 2575.44      80 2573.85      90 2569.89   110.1 2553.69
   200.1 2506.26   220.1 2493.97   240.1 2486.57   250.1 2484.84   260.1 2484.75
   330.2 2487.76   370.2 2486.57   390.2 2483.88   430.2 2474.27   440.1 2471.01
   447.3 2469.85     450 2469.42   462.3 2470.97   479.7 2477.67   489.6 2479.47
   519.3 2491.64   529.2  2494.7   588.6 2505.92   628.2 2517.97   667.7 2532.59
   727.1 2548.39   746.9 2557.74   786.5 2565.99   816.2    2567     836 2570.73
#Mann= 3 , 0 , 0
       0      .1       0   447.3    .045       0   462.3      .1       0
Bank Sta=447.3,462.3
XS Rating Curve= 0 ,0
Exp/Cntr=0.3,0.1

Type RM Length L Ch R = 1 ,7848.1  ,195.6,199.6,196.5
XS GIS Cut Line= 3
     1920399.786      238862.105       1920665.8      239197.118
     1920815.705      239577.048
#Sta/Elev= 30
       0 2599.87      10 2598.92    19.9 2596.56    29.8 2592.67    59.7  2577.3
    69.6  2569.4    89.5 2549.32    99.5 2540.93   109.4 2534.81   129.3 2527.77
   139.3 2526.37   149.2 2522.55   169.1 2512.19   228.8 2489.89   238.8 2487.29
   258.7  2485.4   368.1 2466.98     388 2465.65   417.8 2460.59   420.3  2460.6
   435.3 2461.77   477.6 2468.74   487.6 2469.15   507.5 2473.56   607.1 2479.84
   706.7 2489.91   736.6 2497.57   786.4 2513.28   806.3 2515.96   836.2 2524.72
#Mann= 3 , 0 , 0
       0      .1       0   420.3    .045       0   435.3      .1       0
Bank Sta=420.3,435.3
XS Rating Curve= 0 ,0
Exp/Cntr=0.3,0.1

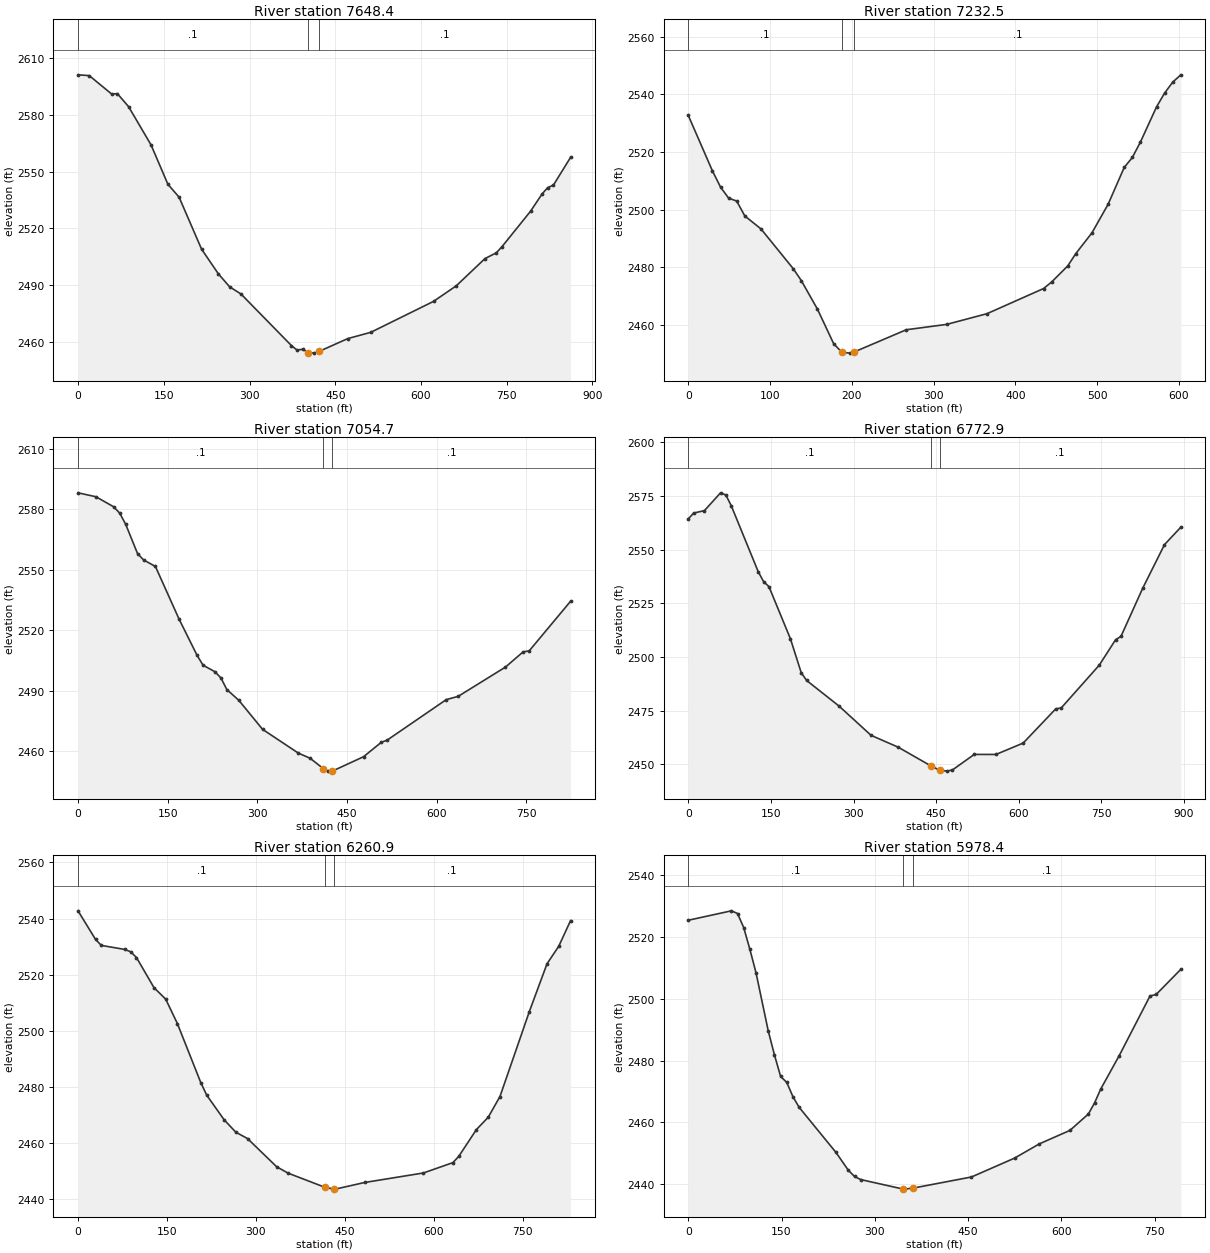
Type RM Length L Ch R = 1 ,7648.4  ,420.1,415.6,410.7
XS GIS Cut Line= 3
     1920275.022      238913.809     1920496.841      239296.215
     1920702.678       239661.78
#Sta/Elev= 30
       0 2601.11    19.6  2600.7    58.9 2590.94    68.8 2591.17    88.4  2584.3
   127.7 2564.08   157.2 2543.27   176.8 2536.43   216.1 2508.97   245.6 2495.88
   265.2 2489.06   284.9 2485.31   373.3 2458.01   383.1 2455.63     393 2456.04
   402.8 2454.29   412.6 2454.01   422.4 2455.01     472 2461.71     512 2464.99
   621.9 2481.36   661.8 2489.62   711.8 2503.96   731.8 2507.04   741.8 2510.32
   791.7 2529.03   811.7 2538.09   821.7 2541.52   831.6 2542.79   861.6 2557.46
#Mann= 3 , 0 , 0
       0      .1       0   402.8    .045       0   422.4      .1       0
Bank Sta=402.8,422.4
XS Rating Curve= 0 ,0
Exp/Cntr=0.3,0.1

Type RM Length L Ch R = 1 ,7232.5  ,179.9,178.1,176.6
XS GIS Cut Line= 2
     1920019.301      239286.335     1920379.926      239768.815
#Sta/Elev= 30
       0  2532.7    29.6  2513.4    39.5 2507.79    49.4 2503.97    59.2 2502.99
    69.1 2497.82    88.9 2493.32   128.4  2479.5   138.2  2475.4     158 2465.46
   177.8  2453.5   187.7 2450.54   197.5 2450.21   202.7 2450.59   266.6 2458.32
     316 2460.18   365.4  2463.9   434.5 2472.62   444.4 2474.89   464.1 2480.46
     474 2484.76   493.7 2491.94   513.5 2501.86   533.2 2514.65   543.1  2518.1
     553 2523.44   572.7 2535.65   582.6 2540.46   592.5 2544.24   602.4 2546.79
#Mann= 3 , 0 , 0
       0      .1       0   187.7    .045       0   202.7      .1       0
Bank Sta=187.7,202.7
XS Rating Curve= 0 ,0
Exp/Cntr=0.3,0.1

Type RM Length L Ch R = 1 ,7054.7  ,274.3,281.6,288.5
XS GIS Cut Line= 3
     1919724.354      239247.268     1919997.576      239550.833
     1920266.977      239867.361
#Sta/Elev= 30
       0 2588.16    29.9 2586.22    59.8  2581.2    69.7 2578.07    79.7 2572.57
    99.6 2557.99   109.6 2554.88   129.5 2551.62   169.3 2525.35   199.2 2507.52
   209.2 2502.62   229.1  2499.4   239.1 2496.31     249 2490.54     269 2485.23
   308.8 2470.81   368.6 2459.03   388.5 2456.44   410.5  2451.3   418.3 2450.08
   425.5 2450.09   477.7 2457.22   507.4 2464.36   517.3 2465.47   616.2 2485.57
     636 2487.16   715.2  2501.7   744.9 2509.28   754.8  2509.7   824.1 2534.34
#Mann= 3 , 0 , 0
       0      .1       0   410.5    .045       0   425.5      .1       0
Bank Sta=410.5,425.5
XS Rating Curve= 0 ,0
Exp/Cntr=0.3,0.1

Type RM Length L Ch R = 1 ,6772.9  ,522.4,512,504.7
XS GIS Cut Line= 3
     1919531.881      239317.622     1919744.304      239597.559
     1919928.734      240108.033
#Sta/Elev= 30
       0 2564.35     9.8 2567.04    29.3 2568.18    58.6 2576.46    68.3 2575.42
    78.1 2570.39   126.9 2539.78   136.7 2535.12   146.4 2532.81   185.5 2508.46
     205 2492.74   214.8  2489.1   273.3 2477.26   331.9 2463.54     381 2458.04
   441.4 2449.18   456.4 2447.28   469.8 2446.88   479.7 2447.45   519.2 2454.66
   558.6 2454.64     608 2459.94   667.2 2475.89   677.1  2476.3   746.2 2496.23
   775.8 2508.06   785.6 2509.62   825.1 2532.06   864.6 2552.34   894.2 2560.44
#Mann= 3 , 0 , 0
       0      .1       0   441.4    .045       0   456.4      .1       0
Bank Sta=441.4,456.4
XS Rating Curve= 0 ,0
Exp/Cntr=0.3,0.1

Type RM Length L Ch R = 1 ,6260.9  ,278,282.3,283.6
XS GIS Cut Line= 3
     1919066.568      239708.378     1919387.352      239985.687
     1919655.388      240291.879
#Sta/Elev= 30
       0 2542.77    29.6 2532.55    39.4 2530.44    78.9    2529    88.8 2528.17
    98.6 2526.12   128.2 2515.37   147.9 2511.29   167.6 2502.59   207.1 2481.55
     217  2477.1   246.5 2468.28   266.2 2463.86     286 2461.58   335.3  2451.5
     355 2449.21   416.5 2444.22   431.5  2443.6     434 2443.56   483.6 2445.93
   582.8 2449.32   632.5 2453.01   642.4 2455.23   672.2  2464.8     692 2469.16
   711.9 2476.56   761.5 2506.86   791.3 2523.88   811.1 2530.14     831 2539.26
#Mann= 3 , 0 , 0
       0      .1       0   416.5    .045       0   431.5      .1       0
Bank Sta=416.5,431.5
XS Rating Curve= 0 ,0
Exp/Cntr=0.3,0.1

Type RM Length L Ch R = 1 ,5978.4  ,349,338.6,328.2
XS GIS Cut Line= 2
      1918935.78      239857.736     1919421.553      240483.478
#Sta/Elev= 30
       0  2525.3    69.3 2528.34    79.2 2527.47    89.1 2522.95      99 2515.95
   108.9 2508.36   128.7 2489.47   138.6 2481.79   148.5 2474.86   158.4 2472.92
   168.3 2468.33   178.2 2464.91   237.6  2450.3   257.4 2444.56   267.4 2442.55
   277.3 2441.55   345.8 2438.47   346.6 2438.46   360.8 2438.76   455.5 2442.38
   524.8 2448.47   564.4 2453.05   613.9 2457.43   643.6 2462.73   653.5 2466.29
   663.4 2470.78   693.2 2481.59   742.7 2500.84   752.6 2501.33   792.2 2509.44
#Mann= 3 , 0 , 0
       0      .1       0   345.8    .045       0   360.8      .1       0
Bank Sta=345.8,360.8
XS Rating Curve= 0 ,0
Exp/Cntr=0.3,0.1

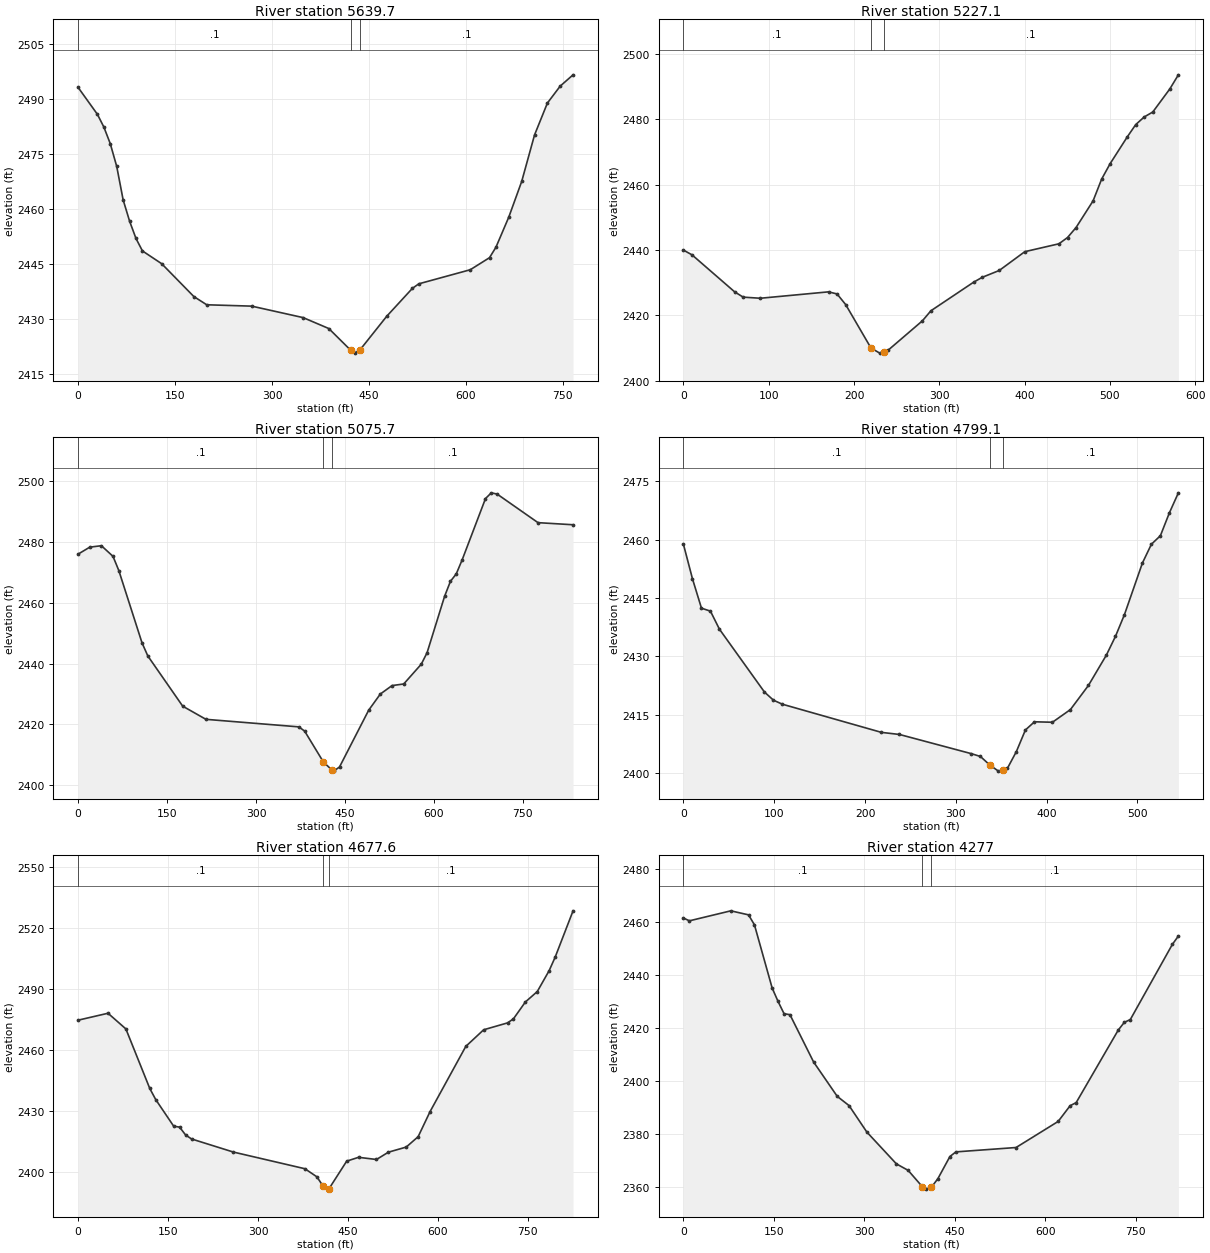
Type RM Length L Ch R = 1 ,5639.7  ,409.8,412.6,415.3
XS GIS Cut Line= 2
     1918551.552      240209.853     1919240.966      240543.582
#Sta/Elev= 30
       0 2493.07    29.8 2485.74    39.8 2482.26    49.7 2477.74    59.7 2471.51
    69.6 2462.41    79.6 2456.59    89.5 2451.87    99.5 2448.47   129.3 2444.98
     179 2436.03     199 2433.78   268.6 2433.41   348.2 2430.28   387.9  2427.3
   421.5 2421.43   427.7 2420.59   436.5 2421.55   477.5 2430.64   517.3 2438.27
   527.2  2439.5   606.8 2443.34   636.6 2446.63   646.6 2449.49   666.5 2457.73
   686.4 2467.42   706.3 2480.12   726.2 2488.82     746 2493.44   765.9 2496.52
#Mann= 3 , 0 , 0
       0      .1       0   421.5    .045       0   436.5      .1       0
Bank Sta=421.5,436.5
XS Rating Curve= 0 ,0
Exp/Cntr=0.3,0.1

Type RM Length L Ch R = 1 ,5227.1  ,147.5,151.3,153.6
XS GIS Cut Line= 2
      1918448.36      240438.194     1918937.975      240749.967
#Sta/Elev= 30
       0 2439.96      10 2438.52      60 2427.19      70 2425.57    90.1 2425.23
   170.1 2427.19   180.1 2426.55   190.2  2423.3   219.9 2409.99   230.2 2408.43
   234.9 2408.87   240.2 2409.37   280.2 2418.32   290.2  2421.4   340.3 2430.15
   350.3 2431.63   370.3 2433.73   400.3 2439.49   440.3  2441.9   450.4 2443.82
   460.4 2446.88   480.4 2455.06   490.4  2461.7   500.4 2466.45   520.4  2474.6
   530.4  2478.4   540.4 2480.74   550.4 2482.25   570.4 2489.32   580.4 2493.63
#Mann= 3 , 0 , 0
       0      .1       0   219.9    .045       0   234.9      .1       0
Bank Sta=219.9,234.9
XS Rating Curve= 0 ,0
Exp/Cntr=0.3,0.1

Type RM Length L Ch R = 1 ,5075.7  ,264.5,276.6,290.2
XS GIS Cut Line= 3
     1918250.257      240403.533     1918561.159      240687.593
     1918884.275      240945.667
#Sta/Elev= 30
       0 2476.09    19.6 2478.38    39.2 2478.85    58.8 2475.34    68.6 2470.66
   107.7 2446.88   117.5 2442.56   176.3 2426.04   215.5  2421.7   372.2 2419.22
     382 2417.82   413.6 2407.66   428.6 2404.91     431 2404.65   440.8 2406.02
     490 2424.71   509.7 2430.04   529.4 2432.81   549.1 2433.34   578.7 2439.85
   588.5 2443.64     618 2462.18   627.9 2467.13   637.7 2469.58   647.6 2474.17
     687 2494.37   696.8 2496.26   706.7 2495.84   775.6 2486.44   834.7 2485.75
#Mann= 3 , 0 , 0
       0      .1       0   413.6    .045       0   428.6      .1       0
Bank Sta=413.6,428.6
XS Rating Curve= 0 ,0
Exp/Cntr=0.3,0.1

Type RM Length L Ch R = 1 ,4799.1  ,122.1,121.4,119.9
XS GIS Cut Line= 2
     1918246.366      240506.257     1918408.839      241026.611
#Sta/Elev= 30
       0 2458.75     9.9 2449.93    19.8 2442.38    29.7 2441.61    39.6 2436.98
    89.2 2420.82    99.1 2418.73     109 2417.69     218 2410.46   237.9 2409.92
   317.2 2404.98   327.1 2404.26   337.4 2402.07   346.9  2400.5   352.4 2400.91
   356.8 2401.23   366.7 2405.54   376.6 2411.07   386.6 2413.18   406.4 2413.06
   426.2 2416.32     446 2422.51   465.8 2430.32   475.8 2435.13   485.7 2440.72
   505.5 2453.99   515.4 2458.81   525.3    2461   535.2 2466.88   545.1 2472.02
#Mann= 3 , 0 , 0
       0      .1       0   337.4    .045       0   352.4      .1       0
Bank Sta=337.4,352.4
XS Rating Curve= 0 ,0
Exp/Cntr=0.3,0.1

Type RM Length L Ch R = 1 ,4677.6  ,392.1,400.6,407.7
XS GIS Cut Line= 3
     1918135.366       240460.51     1918227.819      240858.014
     1918379.113       241246.98
#Sta/Elev= 30
       0 2474.71    49.8 2478.11    79.6 2470.41   119.4 2441.19   129.4 2435.69
   159.3 2422.64   169.2 2422.15   179.2 2418.31   189.1 2416.35   258.8 2409.92
   378.2 2401.72   398.2 2397.74   408.1 2393.37     418  2391.7   447.9 2405.44
   467.7 2407.33   497.6 2406.26   517.4 2409.84   547.2 2412.36   567.1 2417.46
     587  2429.8   646.6 2461.83   676.4 2469.99   716.2 2473.37   726.1 2475.38
     746 2483.66   765.8 2488.76   785.7 2499.09   795.7 2505.71   825.5 2528.43
#Mann= 3 , 0 , 0
       0      .1       0   408.1    .045       0     418      .1       0
Bank Sta=408.1,418
XS Rating Curve= 0 ,0
Exp/Cntr=0.3,0.1

Type RM Length L Ch R = 1 ,4277    ,416.1,401.8,392.1
XS GIS Cut Line= 3
      1917865.06      240537.352     1917849.254       240949.01
     1917861.579      241357.716
#Sta/Elev= 30
       0  2461.4     9.8 2460.35    78.5 2464.12   107.9  2462.6   117.7 2458.84
   147.1 2434.99   156.9 2429.94   166.8 2425.33   176.6 2424.96   215.8 2407.13
     255 2394.17   274.6 2390.69   304.1 2380.71   353.1 2368.72   372.7 2366.25
   396.1 2360.12   402.2 2359.19   411.1 2359.88   421.9 2363.12   441.9 2371.49
   451.8 2373.23   551.6 2374.88   621.4 2384.71   641.3 2390.65   651.3 2391.81
   721.1 2419.17   731.1 2422.06   741.1 2423.13   810.9 2451.49   820.8 2454.61
#Mann= 3 , 0 , 0
       0      .1       0   396.1    .045       0   411.1      .1       0
Bank Sta=396.1,411.1
XS Rating Curve= 0 ,0
Exp/Cntr=0.3,0.1