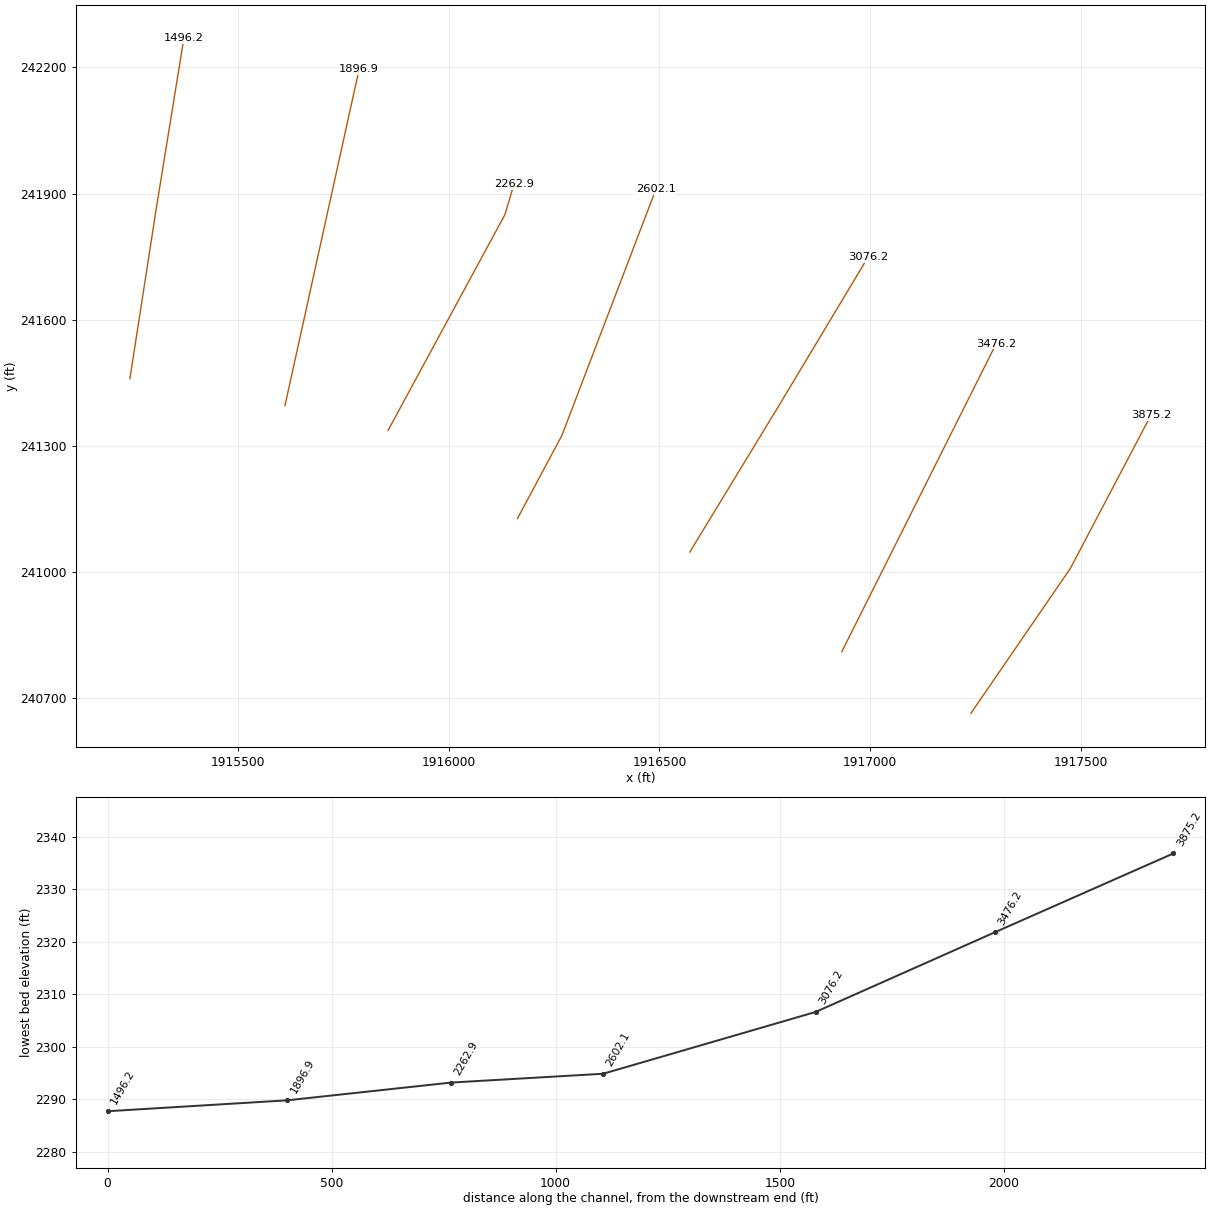
HEC-RAS study BwyrCrk.prj: BwyrCrk

--- BwyrCrk.g01 (geometry) --- (continued)

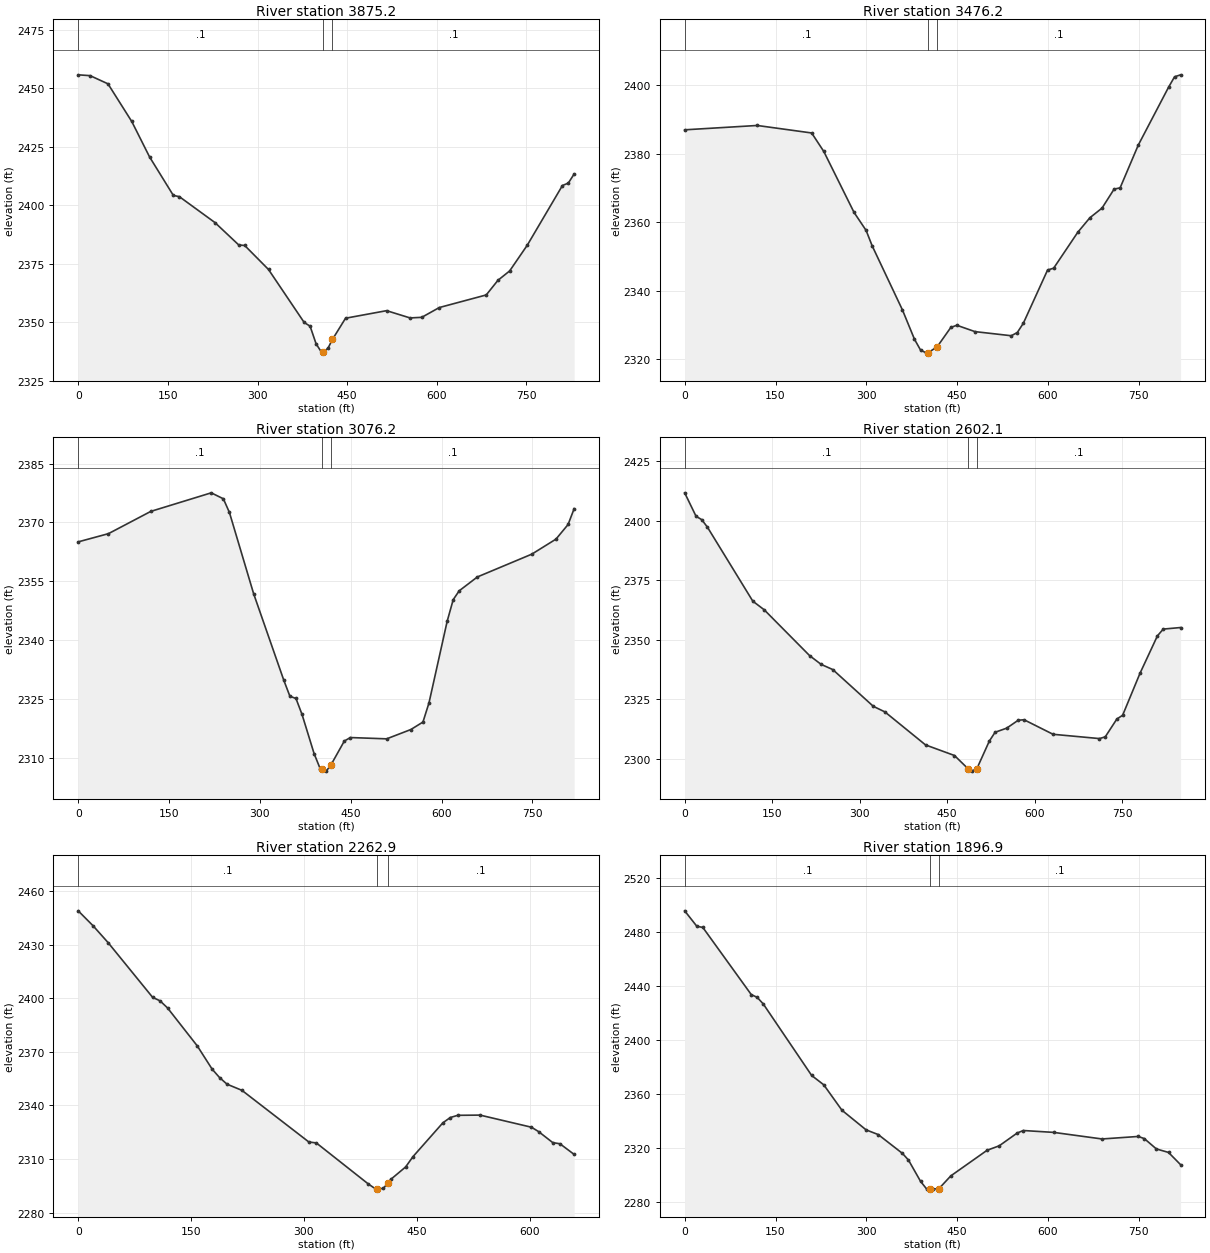
Type RM Length L Ch R = 1 ,3875.2  ,395.7,398.6,399
XS GIS Cut Line= 3
     1917238.918      240664.051     1917475.085       241008.82
     1917666.449      241373.581
#Sta/Elev= 30
       0 2455.77    19.9 2455.42    49.8 2451.92    89.6 2435.82   119.4 2420.67
   159.2 2404.21   169.2  2403.7   228.8 2392.62   268.6 2383.05   278.6 2382.82
   318.4 2372.56   378.1 2349.91     388 2348.32     398  2340.8     408 2336.81
   410.4 2337.32   417.9  2338.9   425.4 2342.68   447.3 2351.73     516 2354.96
   555.2 2351.86   574.8 2352.11   604.2  2356.3   682.7 2361.68   702.3 2367.94
   721.9 2371.95   751.4 2382.96   810.2 2408.46     820 2409.48   829.8 2413.39
#Mann= 3 , 0 , 0
       0      .1       0   410.4    .045       0   425.4      .1       0
Bank Sta=410.4,425.4
XS Rating Curve= 0 ,0
Exp/Cntr=0.3,0.1

Type RM Length L Ch R = 1 ,3476.2  ,401.8,400,398.3
XS GIS Cut Line= 3
     1916932.759      240810.571     1917115.902      241176.834
     1917299.045      241543.098
#Sta/Elev= 30
       0 2386.99   119.8 2388.26   209.7 2386.07   229.7 2380.68   279.7 2362.87
   299.6 2357.62   309.6 2353.12   359.6  2334.4   379.5 2325.83   389.5 2322.68
   399.5 2321.78     402  2321.9     417 2323.64   439.5 2329.28   449.4 2329.92
   479.4 2328.06   539.3 2326.86   549.3 2327.79   559.3 2330.52   599.3 2346.05
   609.3 2346.58   649.2 2357.08   669.2 2361.32   689.2 2364.13   709.1 2369.66
   719.1 2370.05   749.1 2382.54     799  2399.4     809 2402.48     819 2403.05
#Mann= 3 , 0 , 0
       0      .1       0     402    .045       0     417      .1       0
Bank Sta=402,417
XS Rating Curve= 0 ,0
Exp/Cntr=0.3,0.1

Type RM Length L Ch R = 1 ,3076.2  ,470.1,474.1,478
XS GIS Cut Line= 3
      1916572.19      241047.659     1916784.735        241397.7
      1916995.11      241749.027
#Sta/Elev= 30
       0 2365.04    49.9 2367.13   119.9 2372.81   219.7 2377.54   239.7 2376.02
   249.7 2372.54   289.7 2351.82   339.6 2329.73   349.6 2325.68   359.6 2325.12
   369.6 2321.06   389.5 2311.09   399.5 2307.25     402 2307.09   409.5  2306.6
     417 2308.08   439.5 2314.28   449.5 2315.16   509.4 2314.83   549.4 2317.21
   569.3 2319.11   579.3 2324.01   609.3  2344.8   619.3 2350.32   629.2 2352.57
   659.2  2356.1   749.1 2361.91     789 2365.74     809 2369.47     819 2373.51
#Mann= 3 , 0 , 0
       0      .1       0     402    .045       0     417      .1       0
Bank Sta=402,417
XS Rating Curve= 0 ,0
Exp/Cntr=0.3,0.1

Type RM Length L Ch R = 1 ,2602.1  ,341.9,339.2,336.5
XS GIS Cut Line= 3
     1916163.303      241127.334     1916268.692      241324.936
     1916491.638       241909.92
#Sta/Elev= 30
       0 2411.71    19.5 2401.86    29.2 2400.45      39 2397.28   116.8  2366.2
   136.3 2362.59   214.2 2343.32   233.9 2339.66   253.8 2337.49   323.3 2322.05
   343.2  2319.7   412.8 2305.84   462.4 2301.39   485.8 2295.81   492.2 2294.83
   500.8 2295.87   522.1 2307.43     532 2311.15   551.9 2312.88   571.7 2316.21
   581.7  2316.4   631.4  2310.3   710.9  2308.5   720.8 2309.22   740.7 2316.71
   750.6 2318.29   780.4 2335.93   810.2 2351.62   820.2 2354.48     850 2355.14
#Mann= 3 , 0 , 0
       0      .1       0   485.8    .045       0   500.8      .1       0
Bank Sta=485.8,500.8
XS Rating Curve= 0 ,0
Exp/Cntr=0.3,0.1

Type RM Length L Ch R = 1 ,2262.9  ,359.5,365.8,372.2
XS GIS Cut Line= 3
      1915856.21        241336.8     1916133.663       241850.23
      1916155.07      241922.685
#Sta/Elev= 30
       0  2448.9    19.8 2440.51    39.6 2431.17    98.9 2400.49   108.8 2398.52
   118.7 2394.57   158.3 2373.28     178  2360.3   187.9 2355.58   197.8 2351.88
   217.6 2348.44   306.6 2319.52   316.5 2319.01   385.8 2295.97   395.7 2293.15
     397  2293.2   405.6 2293.56     412 2296.84   415.4 2298.58   435.2 2305.56
   445.1  2311.4   484.7 2330.26   494.6 2333.23   504.5 2334.46   534.1 2334.58
   602.5 2327.79   611.9 2325.36   630.8 2319.17   640.3 2318.54   659.2 2312.58
#Mann= 3 , 0 , 0
       0      .1       0     397    .045       0     412      .1       0
Bank Sta=397,412
XS Rating Curve= 0 ,0
Exp/Cntr=0.3,0.1

Type RM Length L Ch R = 1 ,1896.9  ,399.5,400.8,402
XS GIS Cut Line= 3
      1915611.62      241395.775     1915699.614      241795.709
     1915787.609      242195.643
#Sta/Elev= 30
       0 2495.71      20 2484.32      30  2483.4   109.9 2433.76   119.8 2431.66
   129.8  2426.8   209.7 2373.88   229.7 2366.95   259.7 2348.15   299.6 2333.62
   319.6 2330.15   359.6 2316.22   369.6 2311.26   389.5 2295.56   399.5 2289.91
   405.1 2289.83   409.5 2289.77   420.1 2290.23   439.5 2299.57   499.4 2318.52
   519.4 2321.82   549.3 2331.34   559.3 2333.14   609.3 2331.76   689.2 2326.89
   749.1 2328.75   759.1 2327.14     779  2319.5     799 2316.93     819 2307.83
#Mann= 3 , 0 , 0
       0      .1       0   405.1    .045       0   420.1      .1       0
Bank Sta=405.1,420.1
XS Rating Curve= 0 ,0
Exp/Cntr=0.3,0.1

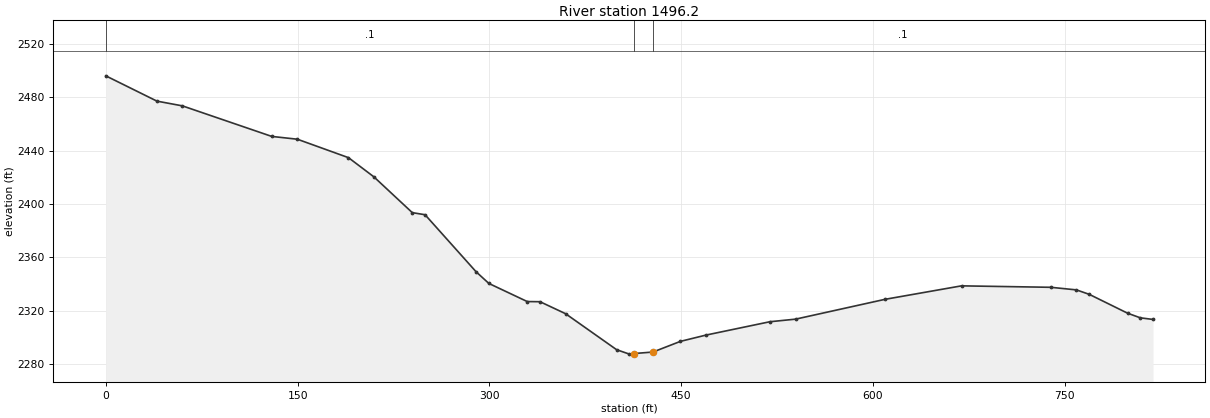
Type RM Length L Ch R = 1 ,1496.2  ,1482.1,1496,1510
XS GIS Cut Line= 3
     1915243.764      241460.022     1915306.346      241864.698
     1915371.786      242268.997
#Sta/Elev= 30
       0 2495.89      40 2476.96    59.9 2473.42   129.8 2450.56   149.8 2448.47
   189.8 2434.67   209.7 2420.29   239.7 2393.54   249.7 2391.97   289.6  2349.3
   299.6 2340.56   329.6 2327.02   339.6  2326.9   359.6 2317.92   399.5 2290.99
   409.5 2287.69   412.9 2288.12   427.9 2289.25   449.4 2297.24   469.4 2301.94
   519.4 2311.93   539.4 2313.85   609.3 2328.67   669.2 2338.77   739.1 2337.68
   759.1 2335.74   769.1 2332.42   799.1  2318.3   809.1 2314.83     819 2313.64
#Mann= 3 , 0 , 0
       0      .1       0   412.9    .045       0   427.9      .1       0
Bank Sta=412.9,427.9
XS Rating Curve= 0 ,0
Exp/Cntr=0.3,0.1

Chan Stop Cuts=-1
Use User Specified Reach Order=0
Composite Channel Slope=5